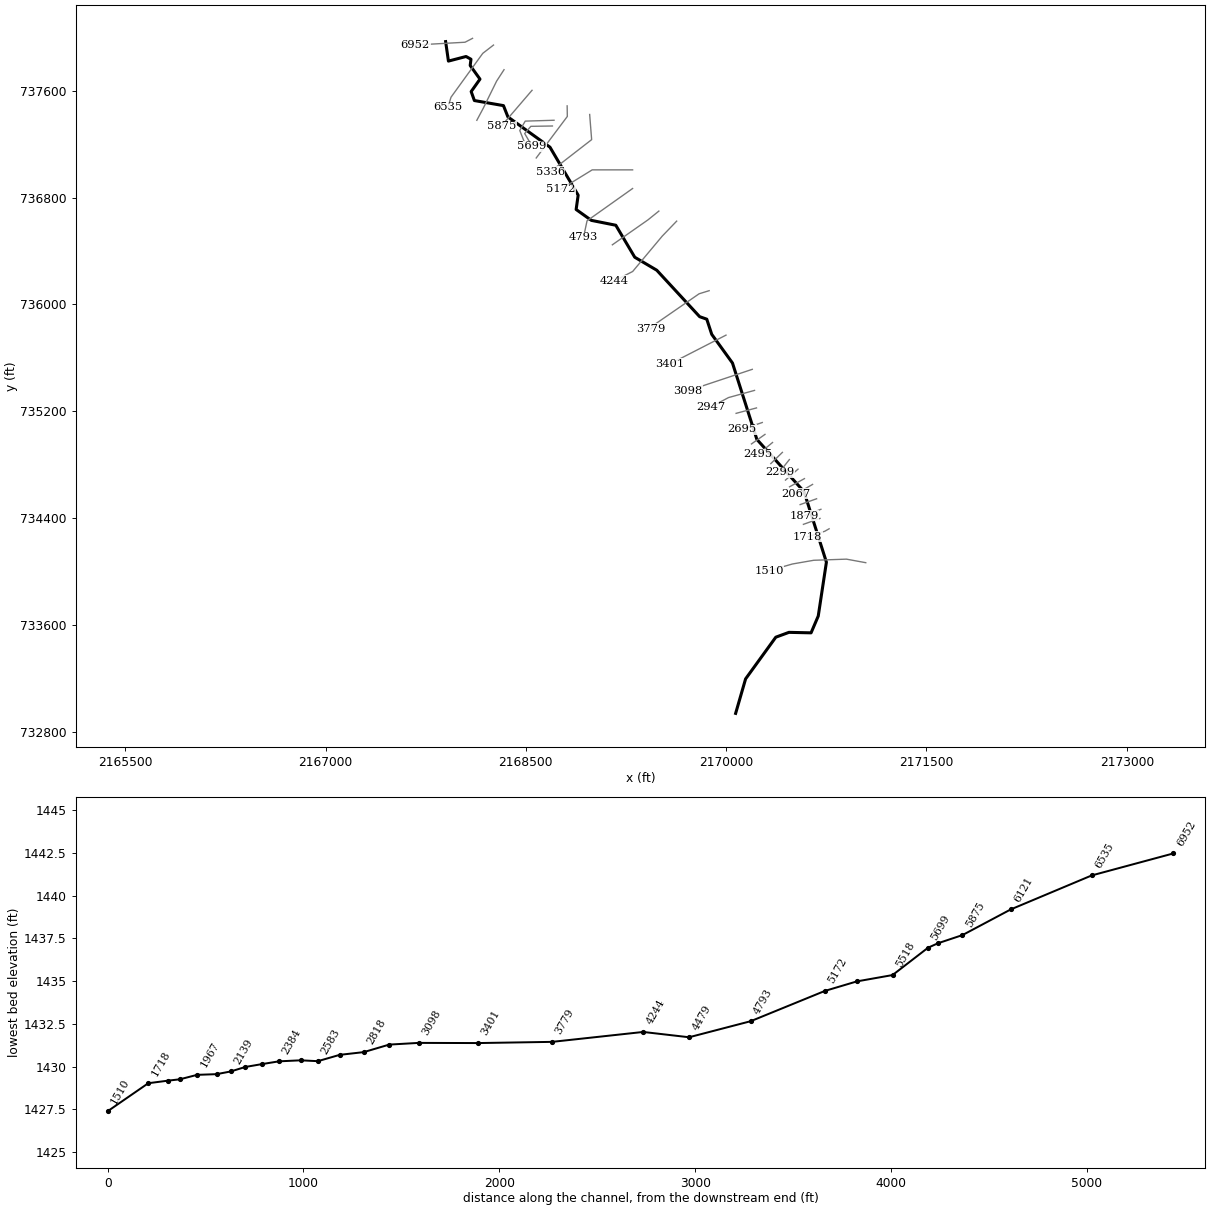
--- BRIDGERN.prj (project) ---

Proj Title=BRIDGERN
Current Plan=p01
Default Exp/Contr=0,0
English Units
Geom File=g01
Flow File=f01
Plan File=p01
BEGIN DESCRIPTION:
---------- MODELED AS PART OF WVEMD CTP PROGRAM, 2023----------
Stream Name: Bridge Run
Flood Zone:  AFH
Upshur County, WV
HEC-RAS Version: RAS 6.3
Vertical Datum: NAVD88
Projection: NAD 1983 StatePlane West Virginia S FIPS 4702 (US Feet)
Terrain: 1-meter LIDAR (FEMA Region III 3DEP collected 2016-2018)
Land Use: 2019 NLCD
Hydrologic Method:
WV SIR2010-5033 regression equations
Additional Model Notes:
None
END DESCRIPTION:
DSS File=dss
DSS Export Rating Curves= 0
DSS Export Rating Curve Sorted= 0
DSS Export Volume Flow Curves= 0
DXF OffsetX= 0
DXF OffsetY= 0
DXF ScaleX= 0
DXF ScaleY= 0

--- BRIDGERN.p01 (plan) ---

Plan Title=Floodplain
Program Version=6.31
Short Identifier=Floodplain
Geom File=g01
Flow File=f01
Subcritical Flow
K Sum by GR= 0
Std Step Tol= 0.01
Critical Tol= 0.01
Num of Std Step Trials= 20
Max Error Tol= 0.3
Flow Tol Ratio= 0.001
Split Flow NTrial= 30
Split Flow Tol= 0.02
Split Flow Ratio= 0.02
Log Output Level= 0
Friction Slope Method= 1
Unsteady Friction Slope Method= 2
Unsteady Bridges Friction Slope Method= 1
Parabolic Critical Depth
Global Vel Dist= 0 , 0 , 0
Global Log Level= 0
CheckData=True
Encroach Param=-1 ,0,0, 0
Computation Interval=0.1SEC
Output Interval=1SEC
Instantaneous Interval=Max Profile
Mapping Interval=1HOUR
Computation Time Step Use Courant=        0
Computation Time Step Use Time Series=    0
Computation Time Step Count To Double=0
Computation Time Step Max Doubling=0
Computation Time Step Max Halving=0
Computation Time Step Residence Courant=0
Run HTab= 0
Run UNet= 0
Run Sediment= 0
Run PostProcess= 0
Run WQNet= 0
Run RASMapper=-1
UNET Theta= 0
UNET Theta Warmup= 0
UNET ZTol= 0
UNET ZSATol= 0
UNET MxIter= 0
UNET Max Iter WO Improvement= 0
UNET MaxInSteps= 0
UNET DtIC= 0
UNET DtMin= 0
UNET MaxCRTS= 0
UNET WFStab= 0
UNET SFStab= 0
UNET WFX= 1
UNET SFX= 1
UNET Gravity=32.17405
UNET 1D Methodology=Finite Difference
UNET DSS MLevel= 1
UNET Pardiso=0
UNET DZMax Abort= 0
UNET Use Existing IB Tables= 0
UNET Froude Reduction=False
UNET Froude Limit= 0
UNET Froude Power= 0
UNET D1 Cores= 0
UNET WindReference=Eulerian
UNET WindDragFormulation=Hsu (1988)
UNET D2 Coriolis=0
UNET D2 Cores= 0
UNET D2 Theta= 1
UNET D2 Theta Warmup= 1
UNET D2 Z Tol= 0.01
UNET D2 Volume Tol= 0.01
UNET D2 Max Iterations= 20
UNET D2 Equation= 0
UNET D2 RampUpFraction=0.1
UNET D2 TimeSlices= 1
UNET D2 Turbulence Formulation=Non-Conservative (original)
UNET D2 Eddy Viscosity=0.3
UNET D2 Transverse Eddy Viscosity=0.1
UNET D2 Smagorinsky Mixing=0
UNET D2 BCVolumeCheck=0
UNET D2 Cores=0
UNET D2 SolverType=PARDISO (Direct)
UNET D2 Minimum Iterations= 3
UNET D2 Maximum Iterations= 30
UNET D2 Restart Number= 10
UNET D2 Relaxation Coeff=1.3
UNET D2 SOR Precondition Iterations= 10
UNET D2 ILUT Maximum Fill= 8
UNET D2 ILUT Tolerance=1E-08
UNET D2 Convergence Tolerance=0.00001
UNET D1D2 MaxIter= 0
UNET D1D2 ZTol=0.01
UNET D1D2 QTol=0.1
UNET D1D2 MinQTol=1
DSS File=dss
Write IC File= 0
Write IC File at Fixed DateTime=0
Write IC File at Sim End=0
Echo Input=False
Echo Parameters=False
Echo Output=False
Write Detailed= 0
HDF Write Warmup=0
HDF Write Time Slices=0
HDF Flush=0
HDF Compression= 1
HDF Chunk Size= 1
HDF Spatial Parts= 1
HDF Use Max Rows=0
HDF Fixed Rows= 1
Calibration Method= 0
Calibration Iterations= 20
Calibration Max Change=0.05
Calibration Tolerance=0.2
Calibration Maximum=1.5
Calibration Minimum=0.5
Calibration Optimization Method= 1
WQ AD Non Conservative
WQ ULTIMATE=-1
WQ Max Comp Step=1HOUR
WQ Output Interval=15MIN
WQ Output Selected Increments= 0
WQ Create Restart=0
WQ Fixed Restart=0
WQ System Summary=0
WQ Write To DSS=0
Sorting and Armoring Iterations= 10
XS Update Threshold= 0.02
Bed Roughness Predictor= 0
Hydraulics Update Threshold= 0.02
Energy Slope Method= 1
Volume Change Method= 1
Sediment Retention Method= 0
Sediment TS Multiplier= 1
Warm Up Method= 0
XS Weighting Method= 0
Number of US Weighted Cross Sections= 1
Number of DS Weighted Cross Sections= 1
Upstream XS Weight=0
Main XS Weight=1
Downstream XS Weight=0
Number of DS XS's Weighted with US Boundary= 1
Upstream Boundary Weight= 1
Weight of XSs Associated with US Boundary= 0
Number of US XS's Weighted with DS Boundary= 1
Downstream Boundary Weight= 0.5
Weight of XSs Associated with DS Boundary= 0.5
Percentile Method= 0
Sediment Output Level= 3
Mass or Volume Output= 0
Output Increment Type= 1
Profile and TS Output Increment= 1
Transport Output Increment 1
XS Output Flag= 0
XS Output Increment= 10
Read HDF5 Sediment Hotstart= 0
Sediment Hotstart Type= 0
Write Gradation File= 0
Read Gradation Hotstart= 0
Write HDF5 File= 1
Write Binary Output= 1
Write DSS Sediment File= 0
DSS Sediment Output Type= 1
SV Curve= 0
Specific Gage Flag= 0
Subcell Erosion Methods= 0
Subcell Deposition Methods= 0
Advection Scheme= 1
Matrix Solver= 0
Implicit Weighting Factor= 1
Maximum Outer Loop Convergence Iterations= 5
Convergence Maximum Absolute= 0.001
Convergence RMSE= 0.0001
Grain Fractions Max Abs Error= 0.001
Max Subgrid Regions= 1
Max Subgrid Length Scale= 3.402823E+38
Initial Layer Thickness= 3.402823E+38
Min Layer Thickness= 3.402823E+38
Max Layer Thickness= 3.402823E+38
Number of Layers= 5

--- BRIDGERN.f01 (steady flow) ---

Flow Title=Flows
Program Version=6.31
Number of Profiles= 1
Profile Names=01pct
River Rch & RM=BRIDGERN,Main,6952
     335
River Rch & RM=BRIDGERN,Main,4793
     543
River Rch & RM=BRIDGERN,Main,3098
     641
Boundary for River Rch & Prof#=BRIDGERN,Main            , 1
Up Type= 0
Dn Type= 3
Dn Slope=0.005
DSS Import GetInterval= 0
DSS Import GetPeak= 0
DSS Import FillOption= 0

--- BRIDGERN.g01 (geometry) ---

Geom Title=Geometry
Program Version=6.31

River Reach=BRIDGERN        ,Main
Reach XY= 30
2167899.35965025737967.8755033462167920.27824359737821.932225674
2168052.34294009737856.3291385022168089.08630492737835.725177094
2168083.13421708737788.9375410082168156.50644568737686.862613916
2168090.57449092737593.7735612542168114.64071576737526.496464834
2168332.41160567 737488.465372922168365.83542334737403.732274666
2168680.64417693737177.2048405862168891.66147143736817.897488341
2168876.52337834736710.7005242562168990.55989568736629.229558587
2169173.61891276736592.715195924 2169315.4703351736353.281947762
2169480.35780059736255.9002527592169801.37651551735908.067943171
2169854.74615942735889.3527574992169891.97607183735775.803115845
2170047.24872717735561.0085979252170229.73523884734989.367352754
2170583.03308867734597.6663645062170750.55342293734069.894454166
 2170689.4574165733666.4890930062170635.71605417733540.691444337
2170470.02708109733544.3544947512170371.64407575733508.125892669
2170145.46014492 733195.892593252170070.82840443 732937.65820159

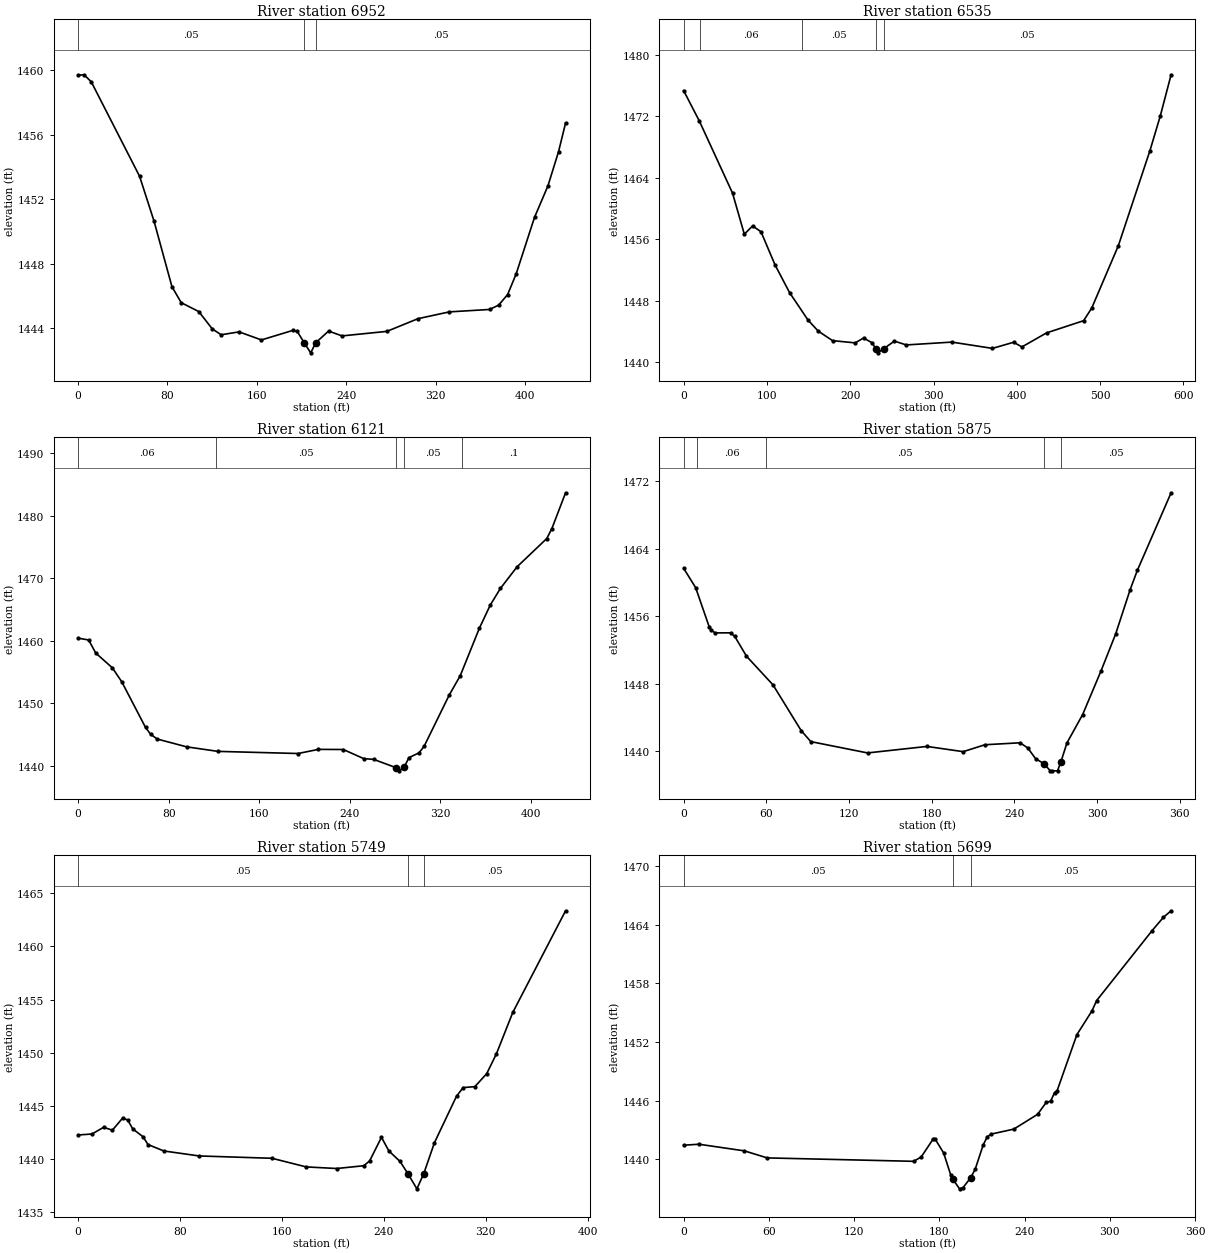
Type RM Length L Ch R = 1 ,6952    ,417.5,417.5,417.5
XS GIS Cut Line= 3
2168100.99117489737992.3162352162168044.51094373737963.102322546
2167672.37064079737942.278046336
#Sta/Elev= 30
       0  1459.7     5.4 1459.72    11.8 1459.28      55 1453.43    67.9 1450.66
      84 1446.58    92.3 1445.59     108 1445.04     120 1443.97     128  1443.6
   144.1 1443.78   164.1 1443.28   192.1 1443.87   196.1 1443.81   202.3 1443.11
   208.2 1442.48   212.71443.107   224.2 1443.83   236.2 1443.53   276.3 1443.81
   304.3  1444.6   332.3 1445.02   368.4 1445.17   376.4 1445.44   384.4 1446.09
     392 1447.36   408.5 1450.88   420.5 1452.83     430 1454.95   436.3 1456.73
#Mann= 3 ,-1,0
       0     .05       0   202.3    .045       0   212.7     .05       0
Bank Sta=202.3,212.7
XS Rating Curve= 0 ,0
Exp/Cntr(USF)=0,0
Exp/Cntr=0.3,0.1

Type RM Length L Ch R = 1 ,6535    ,407.2,413.5,404.9
XS GIS Cut Line= 4
2168257.71146611737941.9470919212168177.28381218737879.820114102
2167939.62191643737551.4648763462167916.48336938737476.738305151
#Sta/Elev= 30
       0 1475.37    18.8 1471.42    58.7 1462.01    72.9 1456.65    82.8 1457.73
    92.9 1456.97   109.8 1452.64   127.2 1449.04   149.3 1445.47   161.6 1444.02
   178.8 1442.78   205.9 1442.49     216 1443.12   226.3  1442.5   230.81441.703
   233.2 1441.19     240 1441.71     253 1442.72   267.3 1442.22     322 1442.59
   370.7 1441.77   396.2 1442.57   406.1 1441.96   435.7 1443.79   480.2 1445.38
     490 1447.04   521.9 1455.16   559.8 1467.54   572.2 1472.05   585.2 1477.43
#Mann= 5 ,-1,0
       0      .1       0      20     .06       0  141.63     .05       0
   230.8    .045       0     240     .05       0
Bank Sta=230.8,240
XS Rating Curve= 0 ,0
Exp/Cntr(USF)=0,0
Exp/Cntr=0.3,0.1

Type RM Length L Ch R = 1 ,6121    ,247.1,246.2,240
XS GIS Cut Line= 4
2168336.65007043737757.5562292962168281.21854383737672.161715338
2168180.84253619 737468.413401332168132.90175642737378.524439268
#Sta/Elev= 30
       0 1460.41     9.3 1460.12    15.6 1458.03    30.3 1455.66    38.6 1453.43
    59.6 1446.13    64.2 1445.02      70 1444.28    95.8 1443.04   123.6 1442.31
   194.4 1441.97   212.4 1442.63   234.4 1442.61   252.3 1441.16   261.2 1441.03
   281.1  1439.7   283.5  1439.2     288 1439.74   292.4 1441.31   301.3 1442.08
   305.8 1443.13   328.1 1451.36   337.7  1454.4   354.6 1461.99   364.3 1465.72
   373.2 1468.36     388 1471.83   414.2 1476.34   418.7 1477.93   430.8 1483.65
#Mann= 5 ,-1,0
       0     .06       0  121.81     .05       0   281.1    .045       0
     288     .05       0  338.94      .1       0
Bank Sta=281.1,288
XS Rating Curve= 0 ,0
Exp/Cntr(USF)=0,0
Exp/Cntr=0.3,0.1

Type RM Length L Ch R = 1 ,5875    ,122,125.5,126.9
XS GIS Cut Line= 2
2168546.39098191737603.2468444232168316.13962458737334.636208672
#Sta/Elev= 30
       0 1461.68     8.7  1459.4    18.5 1454.78    20.1 1454.34    22.9 1454.03
    34.1 1454.04    37.1 1453.62    45.6 1451.28    64.9 1447.87    85.3 1442.47
    92.3 1441.16   133.5 1439.82   176.6 1440.59   202.9 1439.97   218.7 1440.79
   244.2 1441.02   249.8 1440.41   255.4 1439.15   261.5 1438.55   266.1 1437.71
   267.7  1437.7   271.4  1437.7   273.8 1438.74   278.2    1441   289.6 1444.36
     303 1449.55   313.6 1453.92   324.1 1459.16   329.3 1461.43   353.8 1470.62
#Mann= 5 ,-1,0
       0     .07       0      10     .06       0      60     .05       0
   261.5    .045       0   273.8     .05       0
Bank Sta=261.5,273.8
XS Rating Curve= 0 ,0
Exp/Cntr(USF)=0,0
Exp/Cntr=0.3,0.1

Type RM Length L Ch R = 1 ,5749    ,51.9,50.4,47.9
XS GIS Cut Line= 4
2168711.07159877737378.9132397252168495.38697908 737372.46419794
2168454.54304778737302.241298505 2168486.0716965737222.703116492
#Sta/Elev= 30
       0 1442.28    10.9 1442.37      20    1443    26.9 1442.73    34.9 1443.86
    38.9 1443.69    42.9 1442.85    50.9 1442.12    54.9 1441.38    67.2 1440.78
    94.9 1440.31   152.2 1440.09     179 1439.28     203 1439.13   224.2 1439.39
   228.8 1439.84   238.1 1442.06   243.9 1440.78   252.7 1439.79     2591438.614
   265.9 1437.22   271.3 1438.65   279.7 1441.56     297 1445.92   302.2 1446.73
   311.4 1446.82   320.7 1448.04   328.3  1449.9   341.2  1453.8   382.6 1463.34
#Mann= 3 ,-1,0
       0     .05       0     259    .045       0   271.3     .05       0
Bank Sta=259,271.3
XS Rating Curve= 0 ,0
Exp/Cntr(USF)=0,0
Exp/Cntr=0.3,0.1

Type RM Length L Ch R = 1 ,5699    ,179.7,181.1,180.7
XS GIS Cut Line= 5
2168698.96975201737335.9552378732168537.24464516737333.329592329
2168491.38479247737279.5875774562168500.90850597737263.235044894
2168546.88415896737183.757820797
#Sta/Elev= 30
       0 1441.43    10.8 1441.53    42.8 1440.85    58.8 1440.13   161.9 1439.78
   167.2 1440.22   175.7 1442.08   176.8 1442.11     183 1440.64     188 1438.38
   189.61437.929   194.2 1436.96   196.7 1437.09     2021438.092   205.2 1438.96
   210.8 1441.44   213.7 1442.29   216.5 1442.57   232.4 1443.08   249.1 1444.59
   255.2 1445.81   258.3 1445.94   261.1 1446.82   262.9 1447.02   276.8 1452.76
   287.4 1455.19   290.7 1456.25   329.7 1463.41   337.7 1464.78   343.1 1465.45
#Mann= 3 ,-1,0
       0     .05       0   189.6    .045       0     202     .05       0
Bank Sta=189.6,202
XS Rating Curve= 0 ,0
Exp/Cntr(USF)=0,0
Exp/Cntr=0.3,0.1

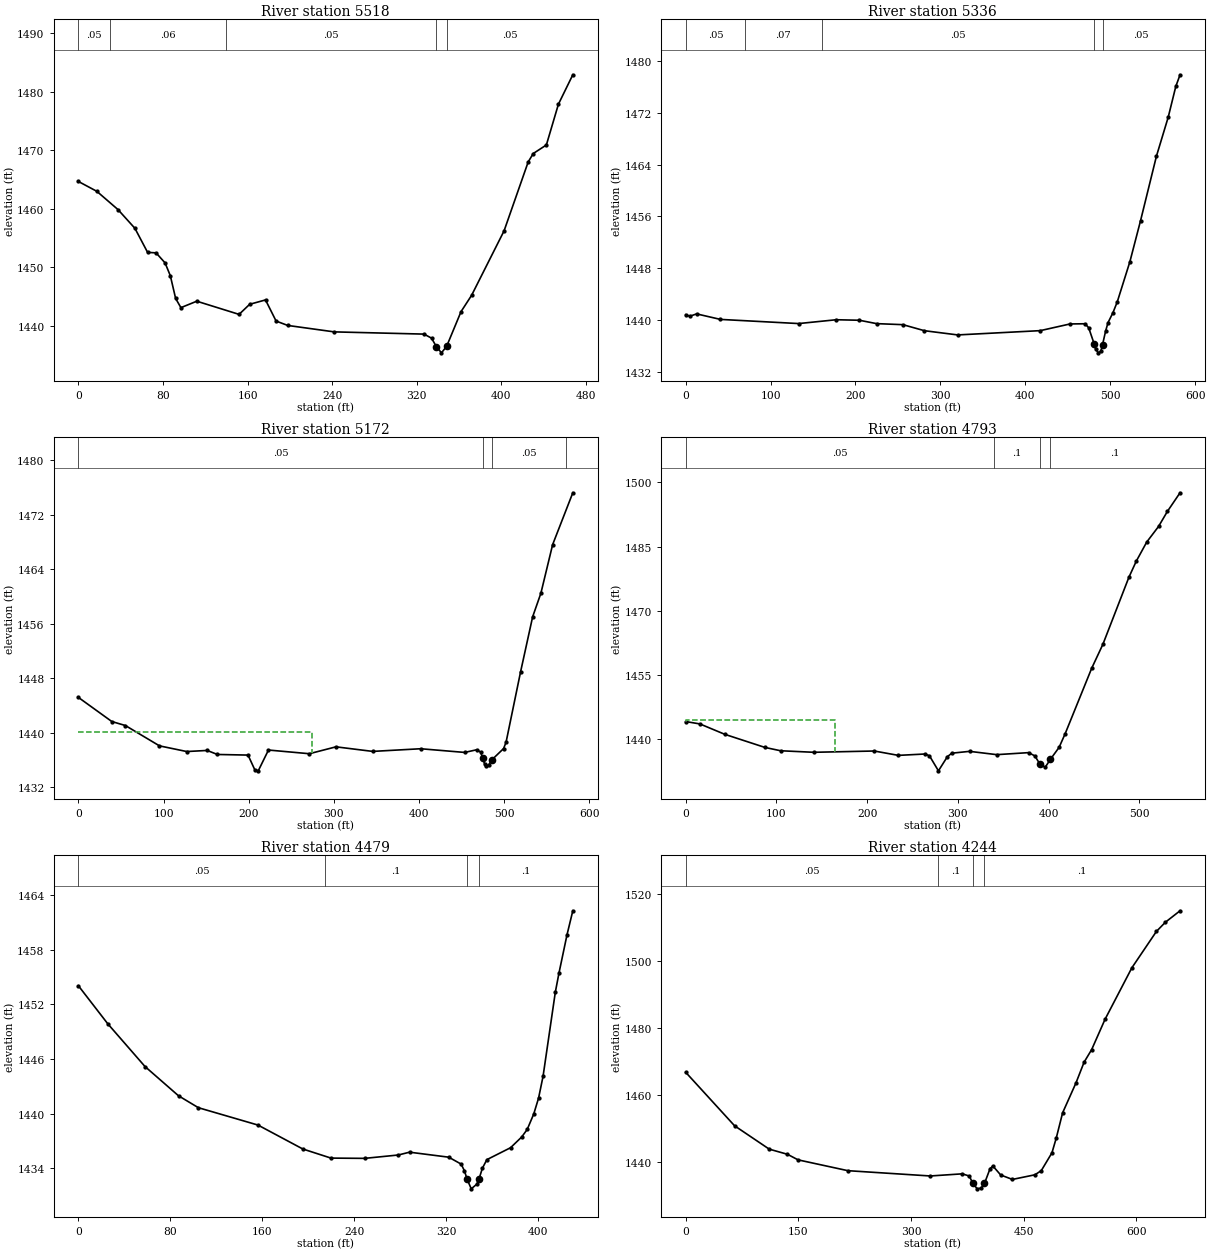
Type RM Length L Ch R = 1 ,5518    ,184.4,182,179
XS GIS Cut Line= 3
2168809.30115236737486.5486437262168810.55006021737407.402756472
 2168577.6996723737096.554138031
#Sta/Elev= 30
       0 1464.63    17.4 1462.95    37.4 1459.83    53.4 1456.63    65.4 1452.52
    73.4 1452.44    81.9 1450.73    86.9 1448.53    91.9 1444.65    96.9 1443.08
   111.9 1444.18   151.9 1441.93   161.9 1443.65   176.9  1444.4   186.9 1440.79
   197.9 1440.04   241.9 1438.94   326.8 1438.56   333.9 1437.87   338.51436.408
   343.3 1435.36   348.2 1436.48   361.8  1442.4   371.8 1445.19   402.5  1456.2
   425.3 1467.97   430.1 1469.41   442.5 1470.87   453.9 1477.84   467.5 1482.86
#Mann= 5 ,-1,0
       0     .05       0      30     .06       0  139.16     .05       0
   338.5    .045       0   348.2     .05       0
Bank Sta=338.5,348.2
XS Rating Curve= 0 ,0
Exp/Cntr(USF)=0,0
Exp/Cntr=0.3,0.1

Type RM Length L Ch R = 1 ,5336    ,164.9,164,162.7
XS GIS Cut Line= 3
2168977.86167407737422.0314420482168992.66817129737233.777405913
2168681.73172959736992.643022548
#Sta/Elev= 30
       0 1440.86     4.9 1440.63    12.9 1440.99      41 1440.14   133.1  1439.5
   177.4 1440.09   204.6 1440.01   224.9 1439.49   255.9 1439.33   281.2  1438.4
   320.4 1437.75   417.7 1438.41   452.7 1439.44   470.5 1439.47   474.7 1438.85
   481.11436.388     483 1435.53   486.1 1434.99     489 1435.24     4911436.248
   494.7 1438.38   497.5 1439.65   503.3 1441.18   508.4 1442.86   523.2 1449.02
   535.8 1455.36   554.5 1465.29   568.4 1471.31   577.3 1476.03   582.3 1477.83
#Mann= 5 ,-1,0
       0     .05       0      70     .07       0     160     .05       0
   481.1    .045       0     491     .05       0
Bank Sta=481.1,491
XS Rating Curve= 0 ,0
Exp/Cntr(USF)=0,0
Exp/Cntr=0.3,0.1

Type RM Length L Ch R = 1 ,5172    ,373.3,378.3,371.2
XS GIS Cut Line= 3
2169299.37418522737007.4495197722168996.89859907737007.449519772
2168759.99464348 736861.49976142
#Sta/Elev= 30
       0 1445.19    39.2 1441.66    55.2 1441.07    95.2 1438.09   127.2 1437.26
   151.2 1437.42   163.2 1436.83   199.2 1436.74   207.2 1434.57   211.2 1434.43
   223.2 1437.48   271.2 1436.94   302.5 1437.95   345.6 1437.28     402 1437.67
   453.7 1437.13   467.8 1437.52   472.5 1437.17   474.81436.295   477.2 1435.39
   479.1  1435.2   481.9 1435.27   485.21435.997   499.4  1437.7   502.3 1438.63
   519.4 1448.98   533.5 1457.01   543.2 1460.47     557  1467.6   580.7  1475.2
#Mann= 4 ,-1,0
       0     .05       0   474.8    .045       0   485.2     .05       0
  572.48     .06       0
#XS Ineff= 2 , 0
          273.78 1440.07
Permanent Ineff=
       F       F
Bank Sta=474.8,485.2
XS Rating Curve= 0 ,0
Exp/Cntr(USF)=0,0
Exp/Cntr=0.3,0.1

Type RM Length L Ch R = 1 ,4793    ,314.1,314.7,316.7
XS GIS Cut Line= 3
2169299.37418522736867.8454030872168958.18030241736625.828559384
2168931.77492599 736501.99644927
#Sta/Elev= 30
       0 1444.17    15.7 1443.61    43.2 1441.18    87.3 1438.13   104.6 1437.35
   141.2 1436.99   207.9 1437.29   234.4 1436.27   263.8 1436.59   268.7 1436.17
   278.6 1432.66   288.4 1435.95   293.3 1436.78   312.9 1437.21   342.8 1436.44
     378 1436.91   384.9 1436.14   390.51434.214   396.3  1433.5   402.11435.377
   411.6 1438.14   418.3 1441.34   447.5  1456.6   459.9 1462.22   488.5 1477.84
   496.7 1481.63   508.2 1486.08   521.2 1489.71   530.9 1493.21   544.9 1497.58
#Mann= 4 ,-1,0
       0     .05       0     340      .1       0   390.5    .045       0
   402.1      .1       0
#XS Ineff= 2 , 0
          165.04 1444.49
Permanent Ineff=
       F       F
Bank Sta=390.5,402.1
XS Rating Curve= 0 ,0
Exp/Cntr(USF)=0,0
Exp/Cntr=0.3,0.1

Type RM Length L Ch R = 1 ,4479    ,230.8,234.3,236.8
XS GIS Cut Line= 3
2169496.00666975736698.7164506322169414.70210357736633.187397288
2169147.73188624736446.308245156
#Sta/Elev= 30
       0 1454.04    25.5 1449.87    57.9 1445.17    87.1 1441.95   104.4 1440.64
   156.3 1438.73   195.3  1436.1   219.8  1435.1   249.1 1435.07   278.4 1435.44
   288.2 1435.75   322.3  1435.2   333.1 1434.44     336 1433.69   338.31432.773
   341.9 1431.72   346.8 1432.24   348.6 1432.78   351.6 1433.99   355.5 1434.93
   376.1 1436.24   385.8 1437.42   390.6 1438.25   396.3 1439.95   400.5  1441.7
   404.4 1444.09   415.1 1453.36   418.3 1455.47   425.3 1459.68   430.3 1462.29
#Mann= 4 ,-1,0
       0     .05       0  214.42      .1       0   338.3    .045       0
   348.6      .1       0
Bank Sta=338.3,348.6
XS Rating Curve= 0 ,0
Exp/Cntr(USF)=0,0
Exp/Cntr=0.3,0.1

Type RM Length L Ch R = 1 ,4244    ,467.8,465.2,460.5
XS GIS Cut Line= 4
2169629.33787162 736623.537705192169521.27002785736511.333496117
2169299.77865662736246.4572171152169159.94255716736175.290023861
#Sta/Elev= 30
       0 1466.83    65.1 1450.85   111.2 1443.88   135.5 1442.34   149.6 1440.68
   215.9 1437.45   325.6 1435.87   368.2 1436.51   377.6 1435.84     382 1433.71
   388.1 1432.03   393.2 1432.26   397.71433.633   405.1 1438.04   408.9 1438.85
   419.3 1436.16   434.9 1434.84   464.8 1436.22   473.3 1437.46   487.5 1442.78
   493.2 1447.15   501.7 1454.72   519.6 1463.71   530.3 1469.84   540.4 1473.61
   558.2 1482.65   593.9 1498.02   626.6 1508.88   638.5 1511.61     658 1515.03
#Mann= 4 ,-1,0
       0     .05       0  335.78      .1       0     382    .045       0
   397.7      .1       0
Bank Sta=382,397.7
XS Rating Curve= 0 ,0
Exp/Cntr(USF)=0,0
Exp/Cntr=0.3,0.1

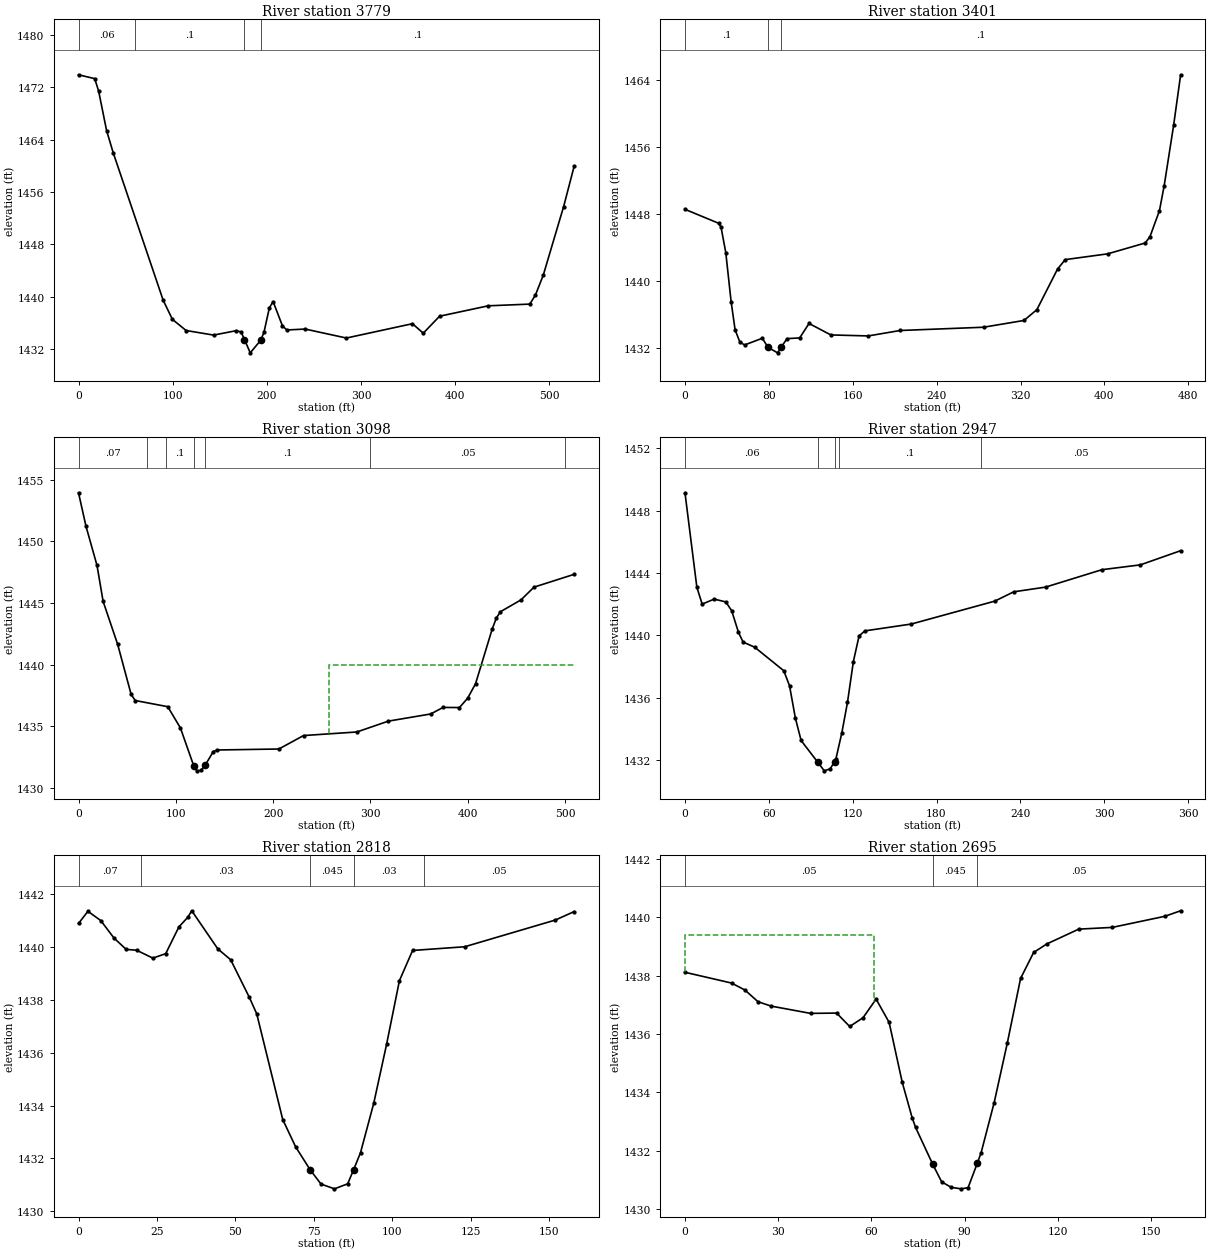
Type RM Length L Ch R = 1 ,3779    ,379,378.6,376.3
XS GIS Cut Line= 4
2169872.62930239736102.7875042682169797.32403008736079.517554683
2169469.39577959 735853.130539122169436.66254699735816.789078711
#Sta/Elev= 30
       0  1473.9    17.2 1473.31    21.4 1471.39    29.8 1465.39    36.8 1462.01
    89.9 1439.47    99.7 1436.56   114.2 1434.86   143.4 1434.16   167.7 1434.84
   172.6 1434.63   176.2 1433.48   182.3 1431.45   193.5 1433.38   196.9 1434.59
   202.6 1438.32   206.6 1439.28   216.5 1435.57   221.2 1434.94   240.6 1435.08
   284.4 1433.71   354.5  1435.9     366 1434.45   383.3 1437.04     435 1438.63
   479.1 1438.89   485.1 1440.28   493.4 1443.31     515 1453.77   526.2 1459.94
#Mann= 4 ,-1,0
       0     .06       0      60      .1       0   176.2    .045       0
   193.5      .1       0
Bank Sta=176.2,193.5
XS Rating Curve= 0 ,0
Exp/Cntr(USF)=0,0
Exp/Cntr=0.3,0.1

Type RM Length L Ch R = 1 ,3401    ,304.4,302.6,301.1
XS GIS Cut Line= 2
2169998.74188951735769.9000186922169578.17926653735554.012809785
#Sta/Elev= 30
       0 1448.53    32.2 1446.86    34.4 1446.39    38.9 1443.37      44  1437.5
    47.8 1434.13    52.3 1432.68    56.8 1432.32    73.7 1433.12    79.3 1432.03
    88.3 1431.38    91.6 1432.02    97.3 1433.08   109.4 1433.16   118.3 1434.89
   139.1 1433.52   174.8  1433.4   205.2 1434.05   284.7 1434.44   323.3 1435.25
   335.6 1436.54   355.3 1441.39   362.6 1442.52   403.1 1443.21     439 1444.51
   443.5 1445.28   452.5 1448.37     457 1451.35     466 1458.56   472.7 1464.61
#Mann= 3 ,-1,0
       0      .1       0    79.3    .045       0    91.6      .1       0
Bank Sta=79.3,91.6
XS Rating Curve= 0 ,0
Exp/Cntr(USF)=0,0
Exp/Cntr=0.3,0.1

Type RM Length L Ch R = 1 ,3098    ,151,150.6,149.9
XS GIS Cut Line= 2
2170195.50675093735513.8775839432169712.34959436735352.825198422
#Sta/Elev= 30
       0 1453.93     7.7 1451.21      19 1448.04    25.3 1445.12    40.2 1441.65
    54.1 1437.58    58.3 1437.09    91.7 1436.59   104.7 1434.87   118.41431.795
   121.6 1431.39   125.8 1431.42   130.41431.881   138.4 1432.94   142.3 1433.08
   205.9 1433.16   231.2 1434.25     286 1434.54   318.4 1435.42   361.9    1436
   374.6 1436.53   391.4 1436.52   399.9 1437.28     408 1438.46   425.1 1442.89
   429.4 1443.79   433.6 1444.29   454.7 1445.25     468 1446.28   509.3 1447.32
#Mann= 7 ,-1,0
       0     .07       0      70     .06       0      90      .1       0
   118.4    .045       0   130.4      .1       0     300     .05       0
     500      .1       0
#XS Ineff= 2 , 0
                          257.58         1439.96
Permanent Ineff=
       F       F
Bank Sta=118.4,130.4
XS Rating Curve= 0 ,0
Exp/Cntr(USF)=0,0
Exp/Cntr=0.3,0.1

Type RM Length L Ch R = 1 ,2947    ,129.9,129.8,129.7
XS GIS Cut Line= 3
2170212.32588618735356.1208553982170017.52893792735302.405945449
2169882.78557938735230.739112769
#Sta/Elev= 30
       0 1449.15     8.5 1443.08    12.3    1442    20.9 1442.32    29.2 1442.14
    33.4 1441.58    38.3 1440.18    41.6 1439.56    49.9 1439.23    70.7 1437.72
    74.8 1436.76      79 1434.68    83.1 1433.24    95.11431.835    99.7 1431.29
   103.9 1431.42   107.11431.883     108 1432.05   112.2 1433.71   116.3 1435.69
   120.5 1438.31   124.6 1439.96   128.8 1440.28     162 1440.72   221.7 1442.19
   235.3 1442.79     258 1443.09   298.4 1444.21   325.9 1444.52   354.7 1445.43
#Mann= 5 ,-1,0
       0     .06       0    95.1    .045       0   107.1     .06       0
     110      .1       0  212.07     .05       0
Bank Sta=95.1,107.1
XS Rating Curve= 0 ,0
Exp/Cntr(USF)=0,0
Exp/Cntr=0.3,0.1

Type RM Length L Ch R = 1 ,2818    ,122,122.9,123.6
XS GIS Cut Line= 2
2170227.06988323735224.8591790932170074.40348441735184.256842106
#Sta/Elev= 30
       0 1440.88       3 1441.34     7.1 1440.99    11.3 1440.33    15.2  1439.9
    18.5 1439.87    23.7 1439.57    27.8 1439.74      32 1440.75    34.8 1441.11
    36.1 1441.36    44.4 1439.92    48.5 1439.51    54.4  1438.1    56.8 1437.47
    65.1 1433.47    69.2 1432.44    73.81431.577    77.3 1431.03    81.6 1430.85
    85.8 1431.04    87.71431.573    89.9 1432.22    94.1 1434.08    98.2 1436.31
   102.3 1438.72   106.5 1439.86   123.1    1440     152 1441.01     158 1441.33
#Mann= 5 ,-1,0
       0     .07       0      20     .03       0    73.8    .045       0
    87.7     .03       0     110     .05       0
Bank Sta=73.8,87.7
XS Rating Curve= 0 ,0
Exp/Cntr(USF)=0,0
Exp/Cntr=0.3,0.1

Type RM Length L Ch R = 1 ,2695    ,108.7,111.6,114.3
XS GIS Cut Line= 2
2170270.41012154735115.6598278672170119.39666528735064.423119492
#Sta/Elev= 30
       0 1438.12      15 1437.75    19.3 1437.51    23.5 1437.11    27.7 1436.96
    40.4 1436.71    48.8 1436.72      53 1436.26    57.3 1436.56    61.5  1437.2
    65.7  1436.4    69.9 1434.35    73.1 1433.13    74.2  1432.8    79.71431.538
    82.6 1430.93    85.7 1430.74    88.9 1430.69    91.1 1430.73    94.11431.577
    95.3 1431.93    99.5 1433.65   103.7 1435.68     108 1437.91   112.2  1438.8
   116.4 1439.09   126.7  1439.6   137.5 1439.66   154.4 1440.04   159.5 1440.23
#Mann= 3 ,-1,0
       0     .05       0    79.7    .045       0    94.1     .05       0
#XS Ineff= 2 , 0
           60.85 1439.41
Permanent Ineff=
       F       F
Bank Sta=79.7,94.1
XS Rating Curve= 0 ,0
Exp/Cntr(USF)=0,0
Exp/Cntr=0.3,0.1

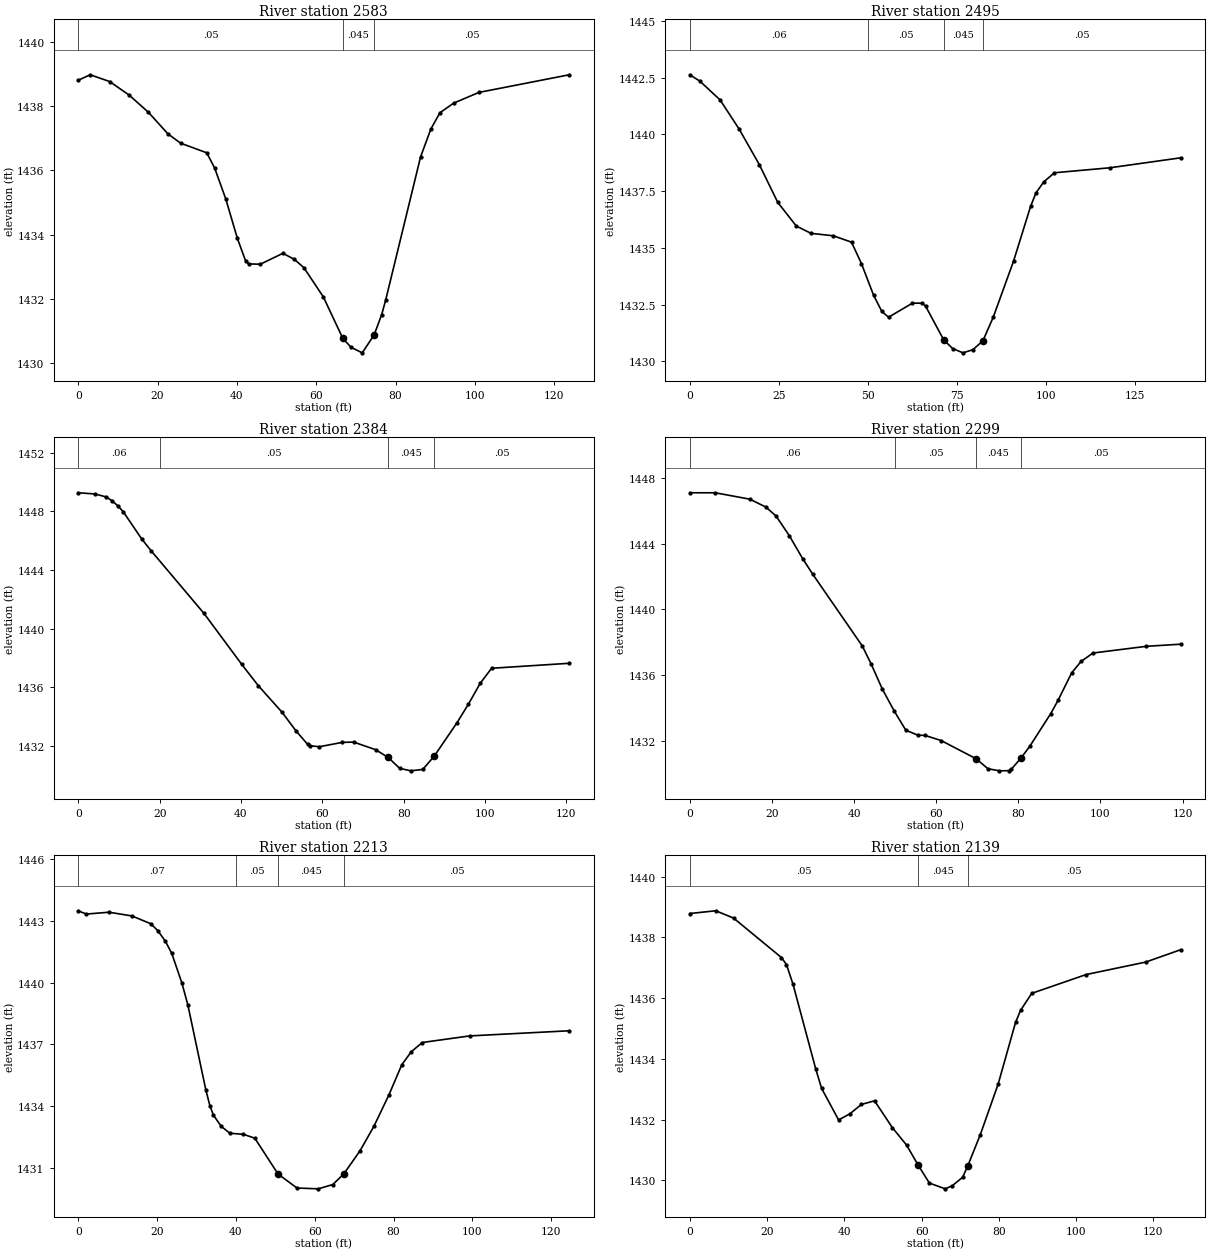
Type RM Length L Ch R = 1 ,2583    ,87.4,88.1,88.7
XS GIS Cut Line= 2
2170290.63513801735026.6697554262170189.51005569734955.208030587
#Sta/Elev= 30
       0 1438.81       3 1438.98     7.9 1438.77    12.8 1438.35    17.7 1437.81
    22.6 1437.14    25.8 1436.85    32.4 1436.55    34.4 1436.07    37.2 1435.11
    40.1 1433.89    42.2 1433.18      43 1433.09    45.9 1433.08    51.6 1433.42
    54.5 1433.23    56.9 1432.97    61.8 1432.06    66.7 1430.77    68.8 1430.49
    71.6 1430.32    74.6 1430.88    76.5 1431.51    77.5 1431.96    86.3 1436.42
    88.9 1437.29    91.2  1437.8    94.7  1438.1     101 1438.43   123.8 1438.98
#Mann= 3 ,-1,0
       0     .05       0    66.7    .045       0    74.6     .05       0
Bank Sta=66.7,74.6
XS Rating Curve= 0 ,0
Exp/Cntr(USF)=0,0
Exp/Cntr=0.3,0.1

Type RM Length L Ch R = 1 ,2495    ,109.9,110.8,111.6
XS GIS Cut Line= 2
2170347.26518411734965.9947060342170240.74676406734878.352968024
#Sta/Elev= 30
       0 1442.63     2.8 1442.35     8.5 1441.52    13.9 1440.22    19.5 1438.67
    24.7    1437    29.9 1435.96      34 1435.64    40.3 1435.53    45.4 1435.25
    48.2  1434.3    51.6 1432.91    53.9  1432.2    55.8 1431.94    62.5 1432.56
    65.3 1432.56    66.2 1432.43    71.3 1430.94    73.8 1430.56    76.7 1430.37
    79.5 1430.51    82.3  1430.9    85.2 1431.94    90.9 1434.41    95.7 1436.83
    97.2 1437.42    99.4 1437.91   102.4 1438.31     118 1438.53   137.9 1438.97
#Mann= 4 ,-1,0
       0     .06       0      50     .05       0    71.3    .045       0
    82.3     .05       0
Bank Sta=71.3,82.3
XS Rating Curve= 0 ,0
Exp/Cntr(USF)=0,0
Exp/Cntr=0.3,0.1

Type RM Length L Ch R = 1 ,2384    ,84.1,85.5,86.9
XS GIS Cut Line= 2
2170421.04145983734892.0280454892170334.34652226734807.987034576
#Sta/Elev= 29
       0 1449.26     4.1 1449.18     6.8 1448.98     8.3 1448.72     9.8 1448.35
    11.1 1447.95    15.6 1446.11    17.9 1445.31    30.9 1441.04    40.2 1437.56
    44.3  1436.1    50.1  1434.3    53.5 1433.04    56.4 1432.11    56.9 1432.03
    59.2 1431.95    64.9 1432.25    67.7 1432.27    73.1 1431.75    76.2 1431.22
      79 1430.48    81.8 1430.31    84.7 1430.41    87.5 1431.31    93.1 1433.59
    95.9 1434.85    98.8 1436.27   101.6  1437.3   120.7 1437.64
#Mann= 4 ,-1,0
       0     .06       0      20     .05       0    76.2    .045       0
    87.5     .05       0
Bank Sta=76.2,87.5
XS Rating Curve= 0 ,0
Exp/Cntr(USF)=0,0
Exp/Cntr=0.3,0.1

Type RM Length L Ch R = 1 ,2299    ,88.7,86.2,83.7
XS GIS Cut Line= 2
2170473.23535082734838.0648700612170398.92540433734744.292794727
#Sta/Elev= 30
       0 1447.12     6.2 1447.12    14.6 1446.73    18.5 1446.25      21  1445.7
    24.2 1444.51    27.5 1443.09    29.9 1442.16      42 1437.77    44.1  1436.7
    46.9 1435.13    49.8 1433.79    52.6 1432.63    55.5 1432.33    57.3 1432.31
    61.2    1432    69.7 1430.89    72.6 1430.28    75.4 1430.15    77.7 1430.16
    78.3 1430.25    80.61430.912    82.8 1431.65    87.9 1433.64    89.7 1434.46
      93 1436.13    95.3 1436.83    98.2 1437.34   111.2 1437.75   119.6 1437.88
#Mann= 4 ,-1,0
       0     .06       0      50     .05       0    69.7    .045       0
    80.6     .05       0
Bank Sta=69.7,80.6
XS Rating Curve= 0 ,0
Exp/Cntr(USF)=0,0
Exp/Cntr=0.3,0.1

Type RM Length L Ch R = 1 ,2213    ,76.5,73.6,70.7
XS GIS Cut Line= 2
2170538.03664814734766.4772856932170444.11167168734684.565969014
#Sta/Elev= 30
       0 1443.49       2 1443.33     7.8 1443.42    13.6 1443.24    18.4 1442.86
    20.2 1442.52    22.1 1442.01    23.7 1441.43    26.3 1439.98    27.8 1438.92
    32.4 1434.76    33.4 1434.02    34.3 1433.56    36.3 1433.01    38.5 1432.68
    41.9 1432.63    44.8 1432.44    50.7  1430.7    55.5 1430.02    60.9 1429.98
    64.6 1430.19    67.4 1430.71    71.5 1431.83      75 1433.01    78.8 1434.53
    82.1 1436.01    84.5 1436.64    87.3 1437.09    99.3 1437.41   124.6 1437.66
#Mann= 4 ,-1,0
       0     .07       0      40     .05       0    50.7    .045       0
    67.4     .05       0
Bank Sta=50.7,67.4
XS Rating Curve= 0 ,0
Exp/Cntr(USF)=0,0
Exp/Cntr=0.3,0.1

Type RM Length L Ch R = 1 ,2139    ,72.1,72.3,72
XS GIS Cut Line= 2
2170586.09128726734695.4874779052170474.69189658734634.327028117
#Sta/Elev= 28
       0 1438.79     6.7 1438.88    11.3 1438.64    23.7 1437.34      25 1437.11
    26.7 1436.46    32.6 1433.66    34.1 1433.03    38.5 1431.99    41.4 1432.19
    44.4  1432.5    47.8 1432.62    52.4 1431.74    56.1 1431.16    59.1  1430.5
      62 1429.91    66.1 1429.72    67.9 1429.82    70.6  1430.1    71.91430.464
    75.2 1431.51    79.8 1433.17    84.3  1435.2    85.6  1435.6    88.5 1436.16
   102.6 1436.78     118 1437.19   127.1  1437.6
#Mann= 3 ,-1,0
       0     .05       0    59.1    .045       0    71.9     .05       0
Bank Sta=59.1,71.9
XS Rating Curve= 0 ,0
Exp/Cntr(USF)=0,0
Exp/Cntr=0.3,0.1

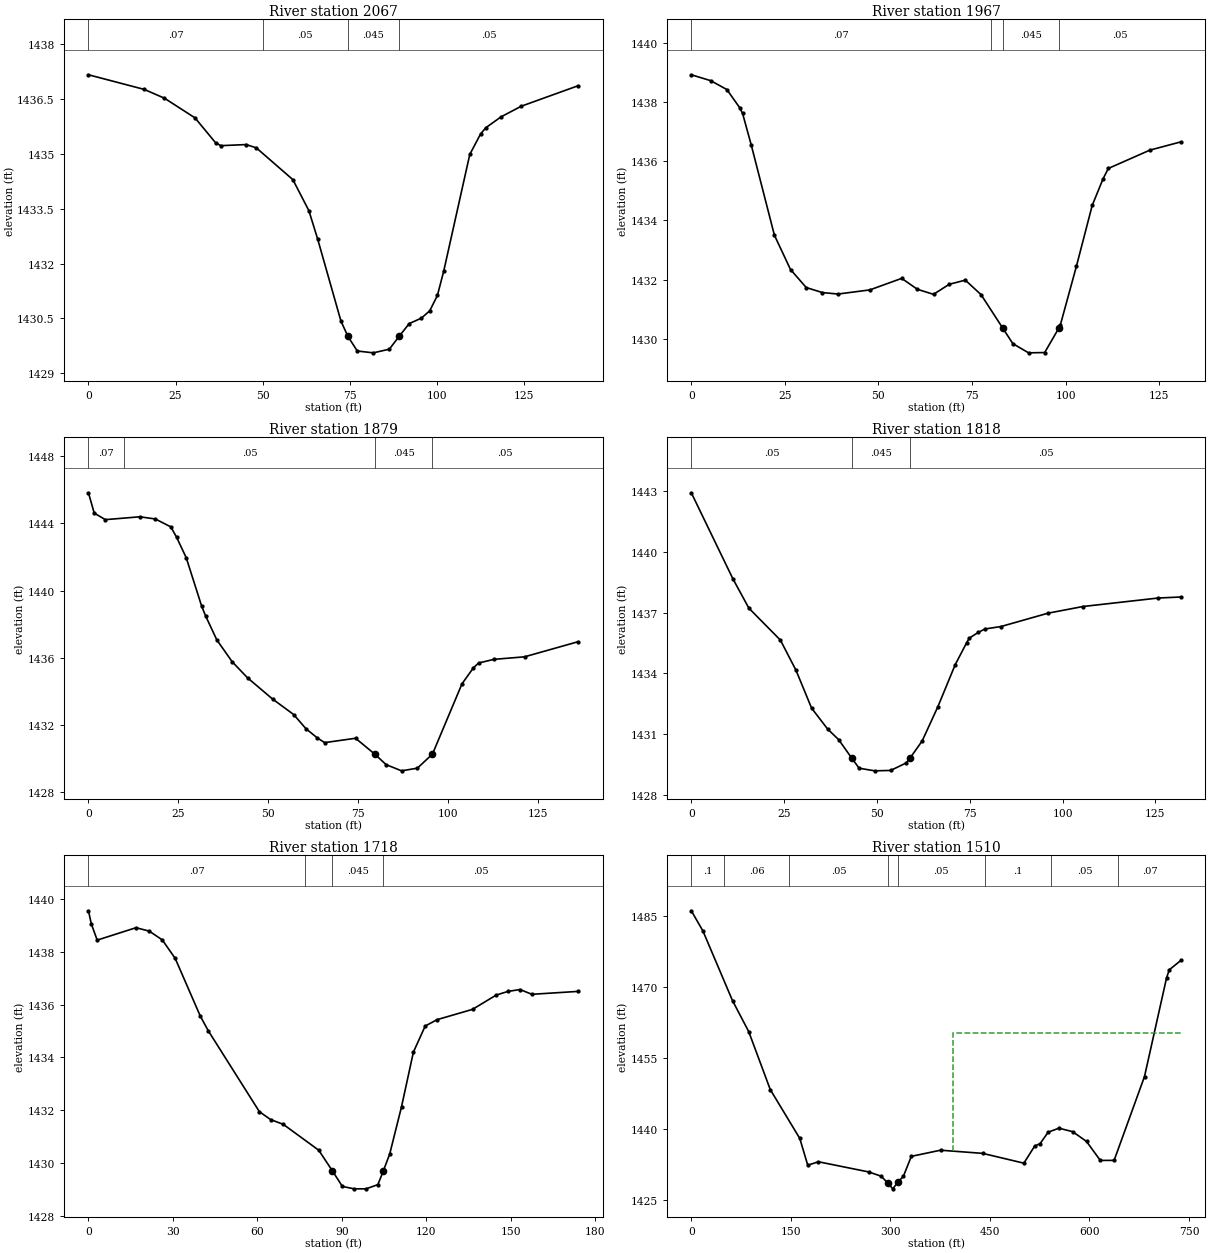
Type RM Length L Ch R = 1 ,2067    ,101.5,99.8,97.1
XS GIS Cut Line= 2
2170647.02511574734652.1455790872170525.20988203734581.922679653
#Sta/Elev= 28
       0 1437.17      16 1436.77    21.8 1436.53    30.6 1435.99    36.5 1435.31
      38 1435.23    45.3 1435.26    48.2 1435.17    58.7  1434.3    63.3 1433.45
    65.8 1432.68    72.5 1430.43    74.5 1430.01    77.2 1429.61    81.8 1429.56
    86.4 1429.66    89.2 1430.01    92.1 1430.36    95.6 1430.51      98 1430.71
   100.2 1431.13     102 1431.79   109.5 1434.99   112.6 1435.55   114.1 1435.72
   118.5 1436.02   124.3 1436.31   140.6 1436.87
#Mann= 4 ,-1,0
       0     .07       0      50     .05       0    74.5    .045       0
    89.2     .05       0
Bank Sta=74.5,89.2
XS Rating Curve= 0 ,0
Exp/Cntr(USF)=0,0
Exp/Cntr=0.3,0.1

Type RM Length L Ch R = 1 ,1967    ,87.4,87.8,87.9
XS GIS Cut Line= 2
2170677.12064407734544.6615493412170553.87228996734500.951377244
#Sta/Elev= 30
       0 1438.93     5.2 1438.73     9.5 1438.43    12.9 1437.82    13.7 1437.62
      16 1436.56    22.2  1433.5    26.5 1432.34    30.7 1431.73      35 1431.56
    39.2 1431.51    47.7 1431.65    56.2 1432.04    60.4 1431.67    64.7  1431.5
    68.9 1431.84    73.2 1431.98    77.4 1431.49    83.21430.357    85.9 1429.83
    90.1 1429.52    94.4 1429.53    98.21430.361    98.6 1430.47   102.9 1432.46
   107.1 1434.51     110 1435.41   111.4 1435.76   122.5 1436.38   130.8 1436.66
#Mann= 4 ,-1,0
       0     .07       0      80     .05       0    83.2    .045       0
    98.2     .05       0
Bank Sta=83.2,98.2
XS Rating Curve= 0 ,0
Exp/Cntr(USF)=0,0
Exp/Cntr=0.3,0.1

Type RM Length L Ch R = 1 ,1879    ,61.1,60.7,60.6
XS GIS Cut Line= 2
2170709.57976792734465.886441756  2170582.277278734417.412250692
#Sta/Elev= 30
       0 1445.82     1.6 1444.61     4.7 1444.22    14.3 1444.39    18.6 1444.26
    22.9 1443.79    24.5 1443.18    27.2 1441.95    31.5 1439.06    32.6 1438.48
    35.7 1437.06      40 1435.75    44.3 1434.79    51.2 1433.54    57.1 1432.61
    60.5 1431.77    63.6 1431.23    65.7 1430.94    74.3  1431.2    79.61430.263
    82.8 1429.63    87.1 1429.26    91.5 1429.42    95.7 1430.26   103.9 1434.44
     107 1435.37   108.5 1435.68   112.8  1435.9   121.3 1436.05   136.2 1436.95
#Mann= 4 ,-1,0
       0     .07       0      10     .05       0    79.6    .045       0
    95.7     .05       0
Bank Sta=79.6,95.7
XS Rating Curve= 0 ,0
Exp/Cntr(USF)=0,0
Exp/Cntr=0.3,0.1

Type RM Length L Ch R = 1 ,1818    ,101.3,100.9,100.7
XS GIS Cut Line= 2
2170702.74725043 734397.372665242170578.47488785734353.202019595
#Sta/Elev= 26
       0 1442.92    11.2 1438.67    15.5 1437.22      24 1435.64    28.2 1434.15
    32.4 1432.28    36.7 1431.25    39.7 1430.72    43.21429.814    45.2 1429.31
    49.4 1429.18    53.7  1429.2    57.9 1429.57      59 1429.83    62.2 1430.66
    66.4 1432.34    71.1 1434.43    74.2 1435.52    74.9 1435.74    77.3 1436.02
    79.1 1436.19    83.4 1436.31    96.1 1436.97   105.5  1437.3   125.8 1437.72
   131.9 1437.77
#Mann= 3 ,-1,0
       0     .05       0    43.2    .045       0      59     .05       0
Bank Sta=43.2,59
XS Rating Curve= 0 ,0
Exp/Cntr(USF)=0,0
Exp/Cntr=0.3,0.1

Type RM Length L Ch R = 1 ,1718    ,210.4,207.6,203.3
XS GIS Cut Line= 3
2170770.87706979734319.8883527962170738.70283525734301.491105708
2170608.55650895734259.294780907
#Sta/Elev= 30
       0 1439.55       1 1439.06     3.1 1438.44    16.9 1438.91    21.6 1438.78
    26.2 1438.45    30.8 1437.75    39.7 1435.57    42.5 1435.02    60.7 1431.95
    64.7 1431.65    69.2 1431.47    81.8 1430.49    86.61429.716    90.2 1429.12
    94.4 1429.03    98.6 1429.03   102.8 1429.19   104.71429.701     107 1430.35
   111.2 1432.14   115.4  1434.2   119.6 1435.19   123.8 1435.43   136.4 1435.82
   144.8 1436.36     149  1436.5   153.3 1436.57   157.5 1436.39   173.9  1436.5
#Mann= 4 ,-1,0
       0     .07       0   77.06     .05       0    86.6    .045       0
   104.7     .05       0
Bank Sta=86.6,104.7
XS Rating Curve= 0 ,0
Exp/Cntr(USF)=0,0
Exp/Cntr=0.3,0.1

Type RM Length L Ch R = 1 ,1510    ,216.1,215.2,213
XS GIS Cut Line= 5
2171045.24348504734065.9846343362170900.54608652734092.512490731
2170655.76632069734084.0718091512170496.59918232734056.338141101
2170319.34486913 734005.69405162
#Sta/Elev= 30
       0 1486.11    17.4 1481.88    62.1 1467.13    86.5  1460.6     119 1448.35
   163.5 1438.03   175.5 1432.37   191.5 1433.11   267.6 1430.95   286.1 1430.06
   296.71428.539   303.6 1427.39   311.71428.849   319.6 1430.04   331.6 1434.25
   375.6 1435.55   439.1 1434.88   501.2 1432.81   517.5 1436.43   525.7 1436.95
   537.8 1439.35     554  1440.2   574.8 1439.46   595.6  1437.4   616.4 1433.39
   637.2  1433.4     683 1451.11   716.3 1471.98   720.4 1473.65   737.9 1475.64
#Mann= 8 ,-1,0
       0      .1       0      50     .06       0  147.11     .05       0
   296.7    .045       0   311.7     .05       0  442.03      .1       0
  542.03     .05       0   643.6     .07       0
#XS Ineff= 2 , 0
                          394.54         1460.28
Permanent Ineff=
       F       F
Bank Sta=296.7,311.7
XS Rating Curve= 0 ,0
Exp/Cntr(USF)=0,0
Exp/Cntr=0.3,0.1