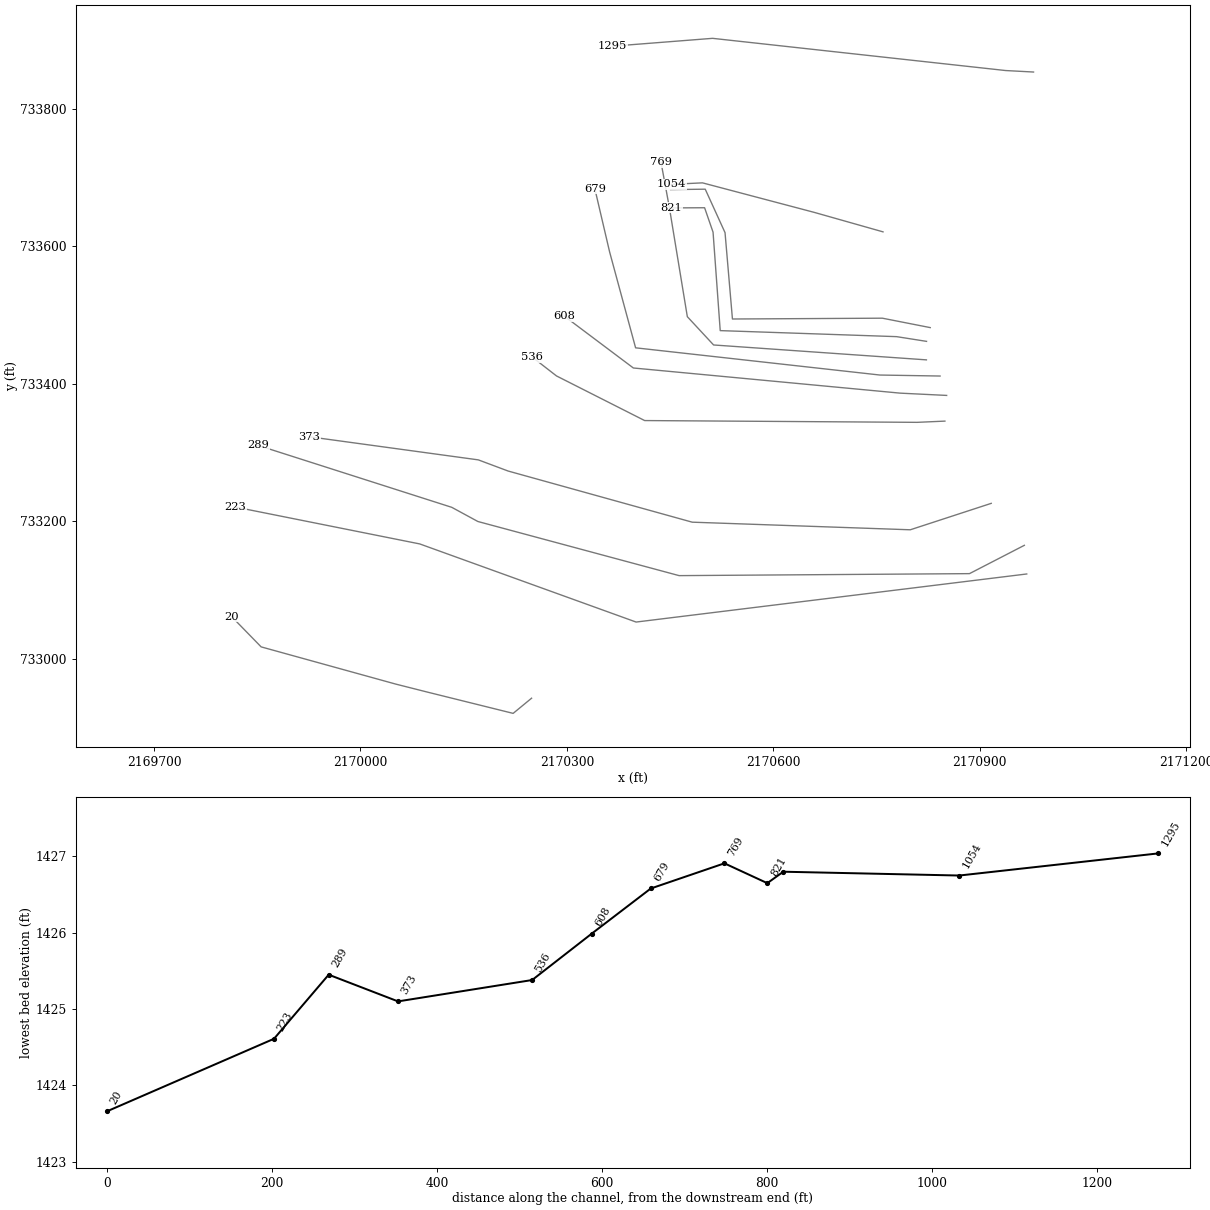
HEC-RAS study BRIDGERN.prj: BRIDGERN

--- BRIDGERN.g01 (geometry) --- (continued)

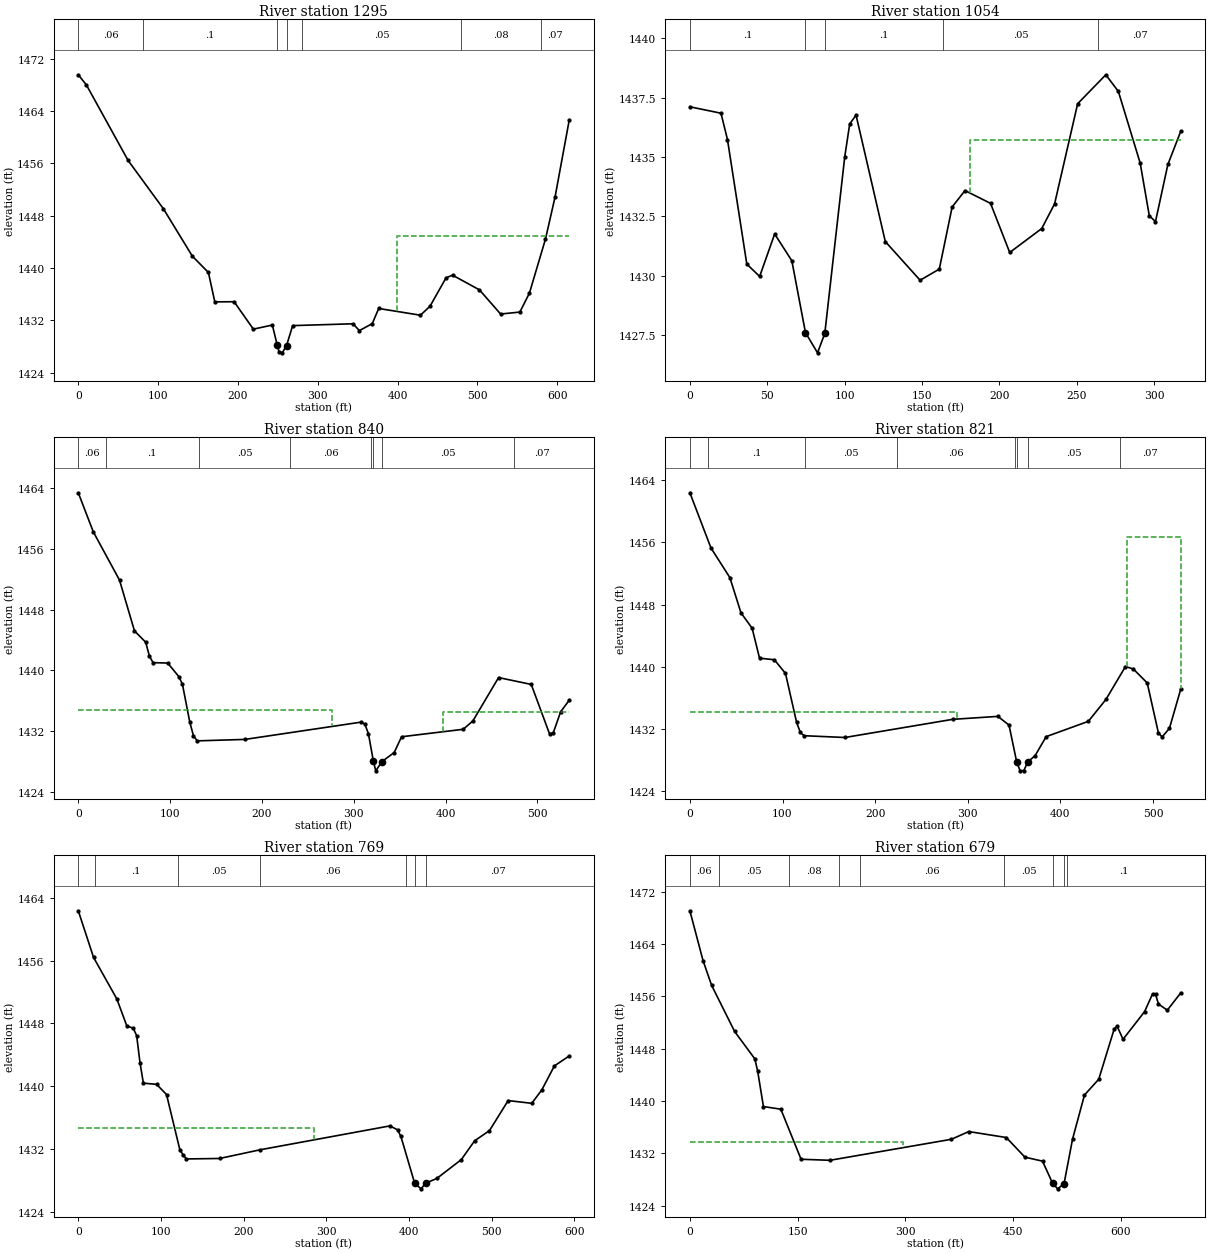
Type RM Length L Ch R = 1 ,1295    ,243.1,241.2,239.4
XS GIS Cut Line= 4
2170978.37259851 733853.251157512170937.81429749733855.416675136
2170511.78294409733902.2323488052170366.40531702733890.818747404
#Sta/Elev= 30
       0 1469.53    10.2 1467.97    62.4 1456.44   106.7 1449.04   142.9 1441.81
     163 1439.32     171 1434.83   195.2 1434.85   219.3 1430.66   243.1 1431.29
   249.2  1428.2   251.5 1427.19   255.5 1427.04   260.91428.161   268.5  1431.2
   344.1 1431.48   352.1 1430.44   368.2  1431.5   376.3 1433.82   428.6 1432.79
   440.6 1434.17   460.7 1438.51   468.8 1438.91   502.5 1436.66     529 1432.97
   553.1 1433.27   565.1 1436.17   585.2 1444.43   597.2 1450.86     615 1462.64
#Mann= 7 ,-1,0
       0     .06       0   80.62      .1       0   249.2    .045       0
   260.9      .1       0  280.62     .05       0  479.21     .08       0
  579.21     .07       0
#XS Ineff= 2 , 0
                          398.59         1444.93
Permanent Ineff=
       F       F
Bank Sta=249.2,260.9
XS Rating Curve= 0 ,0
Exp/Cntr(USF)=0,0
Exp/Cntr=0.3,0.1

Type RM Length L Ch R = 1 ,1054    ,226.4,213.4,201.3
XS GIS Cut Line= 4
2170759.55989134733620.9315127662170659.59532046733649.240063809
2170497.14599755733692.1557343012170451.78382825733690.010226293
#Sta/Elev= 30
       0 1437.12    20.1 1436.85    24.3 1435.74    36.8 1430.49    45.1 1429.97
    54.8 1431.76    65.9 1430.63    74.71427.602    82.5 1426.75    87.2 1427.57
   100.1 1435.02   103.3  1436.4   107.4 1436.77   126.3 1431.44   148.8 1429.81
   161.2 1430.28   169.5  1432.9   177.8 1433.59   194.3 1433.05   206.7 1430.98
   227.4 1431.99   235.7 1433.03   250.6 1437.25   268.8 1438.47   276.9 1437.77
     291 1434.75   296.9 1432.53   300.9 1432.28   308.9 1434.69   317.3  1436.1
#Mann= 5 ,-1,0
       0      .1       0    74.7    .045       0    87.2      .1       0
   163.9     .05       0   263.9     .07       0
#XS Ineff= 2 , 0
                           181.3          1435.7
Permanent Ineff=
       F       F
Bank Sta=74.7,87.2
XS Rating Curve= 0 ,0
Exp/Cntr(USF)=0,0
Exp/Cntr=0.3,0.1

Type RM Length L Ch R = 1 ,840     ,19,19.4,19.6
XS GIS Cut Line= 6
2170828.20361538 733481.751015112170758.59714605733495.445746896
2170540.67881171733494.2627173522170529.91988914733619.798961338
2170501.13051243733682.9606999822170450.81474548733682.337096876
#Sta/Elev= 30
       0 1463.35    16.3 1458.23    44.9 1451.87    61.2 1445.19    73.4 1443.71
    77.4  1441.9    81.4 1441.02    97.4 1440.97   109.4  1439.2   113.4 1438.19
   121.4  1433.2   125.4 1431.42   129.4 1430.74   181.4 1430.93   307.8  1433.2
   311.9 1432.97   315.9 1431.69   321.31428.074   323.9  1426.8   330.71428.021
     344 1429.21     352 1431.28   419.1 1432.26   429.6 1433.35   457.6 1439.06
   493.2 1438.16   513.2 1431.63   517.2 1431.81   525.2 1434.56   534.6 1436.09
#Mann= 8 ,-1,0
       0     .06       0      30      .1       0  130.94     .05       0
  230.94     .06       0  318.86     .05       0   321.3    .045       0
   330.7     .05       0  474.86     .07       0
#XS Ineff= 2 , 0
          276.09 1434.86  397.56         1434.52
Permanent Ineff=
       F       F
Bank Sta=321.3,330.7
XS Rating Curve= 0 ,0
Exp/Cntr(USF)=0,0
Exp/Cntr=0.3,0.1

Type RM Length L Ch R = 1 ,821     ,51,52,53.5
XS GIS Cut Line= 6
2170822.82689746733461.7514510792170779.29255796733468.613319336
2170522.91705338733477.3744881142170512.50747633733620.443865516
2170500.21100899733655.9885993142170451.86150767 733655.75289931
#Sta/Elev= 30
       0 1462.34    22.8 1455.25    43.2 1451.45    55.2 1446.92    67.2 1444.96
    75.2 1441.11    91.2 1440.91   103.2 1439.16   115.2 1432.88   119.2 1431.59
   123.2 1431.16   167.3 1430.93   283.7 1433.26   332.5 1433.64   344.5 1432.52
   352.81427.782   356.5 1426.65   360.6 1426.69   364.6 1427.79   372.6 1428.59
   384.6 1431.04   430.1    1433   449.1 1435.81   470.2 1440.04   478.7 1439.72
   493.7 1437.93   505.7 1431.55   509.7 1430.99   517.7 1432.12     530 1437.19
#Mann= 8 ,-1,0
       0     .06       0      20      .1       0  124.07     .05       0
  224.07     .06       0   350.6     .05       0   352.8    .045       0
   364.6     .05       0  464.04     .07       0
#XS Ineff= 2 , 0
          288.82 1434.24  471.89         1456.72
Permanent Ineff=
       F       F
Bank Sta=352.8,364.6
XS Rating Curve= 0 ,0
Exp/Cntr(USF)=0,0
Exp/Cntr=0.3,0.1

Type RM Length L Ch R = 1 ,769     ,88.4,89.3,90.5
XS GIS Cut Line= 5
2170822.64178941733434.8623851692170513.27485464733456.513549002
2170475.11198852733497.6369411792170448.85122804733657.158688119
2170436.89508031733721.878691594
#Sta/Elev= 30
       0 1462.35    18.5  1456.4    46.6 1451.12    58.6  1447.7    66.6 1447.36
    70.6 1446.43    74.6 1443.01    78.7 1440.38    94.7 1440.23   106.7 1438.93
   122.8  1431.9   126.8 1431.23   130.8 1430.72   170.9 1430.78     220 1431.89
   376.7 1434.93     386 1434.44   390.1 1433.59   406.7 1427.64   414.4 1426.91
   420.3 1427.64   433.6 1428.24   463.1 1430.63   479.3 1433.04   497.2 1434.33
   519.8 1438.16   548.3 1437.81   560.5 1439.52   575.7 1442.58   593.7 1443.85
#Mann= 7 ,-1,0
       0     .06       0      20      .1       0     120     .05       0
     220     .06       0  396.23     .07       0   406.7    .045       0
   420.3     .07       0
#XS Ineff= 2 , 0
          285.35 1434.63
Permanent Ineff=
       F       F
Bank Sta=406.7,420.3
XS Rating Curve= 0 ,0
Exp/Cntr(USF)=0,0
Exp/Cntr=0.3,0.1

Type RM Length L Ch R = 1 ,679     ,61.5,71.4,79.5
XS GIS Cut Line= 5
2170842.51438417733411.3616299512170755.07478284733412.807141889
2170399.91231011733452.3664470292170362.15629047733591.695163829
2170340.66782914733683.569430699
#Sta/Elev= 30
       0 1469.06    18.3 1461.46    30.3 1457.66    62.3 1450.62    90.4 1446.44
    94.4 1444.55   102.4 1439.15   126.6 1438.75   154.8  1431.1     195 1430.94
   364.1 1434.15   388.2 1435.33   440.5 1434.42   466.4 1431.42   490.9 1430.81
     505 1427.42     512 1426.58   520.91427.381   532.7 1434.17   549.3 1440.91
   569.2 1443.33   590.7    1451   594.8 1451.41     603 1449.43     633 1453.65
   644.1 1456.36   648.2  1456.3   652.3 1454.82   664.6 1453.87   683.5 1456.54
#Mann= 9 ,-1,0
       0     .06       0      40     .05       0  137.45     .08       0
  207.45     .05       0  237.45     .06       0  437.45     .05       0
     505    .045       0   520.9     .05       0  524.81      .1       0
#XS Ineff= 2 , 0
          296.02 1433.73
Permanent Ineff=
       F       F
Bank Sta=505,520.9
XS Rating Curve= 0 ,0
Exp/Cntr(USF)=0,0
Exp/Cntr=0.3,0.1

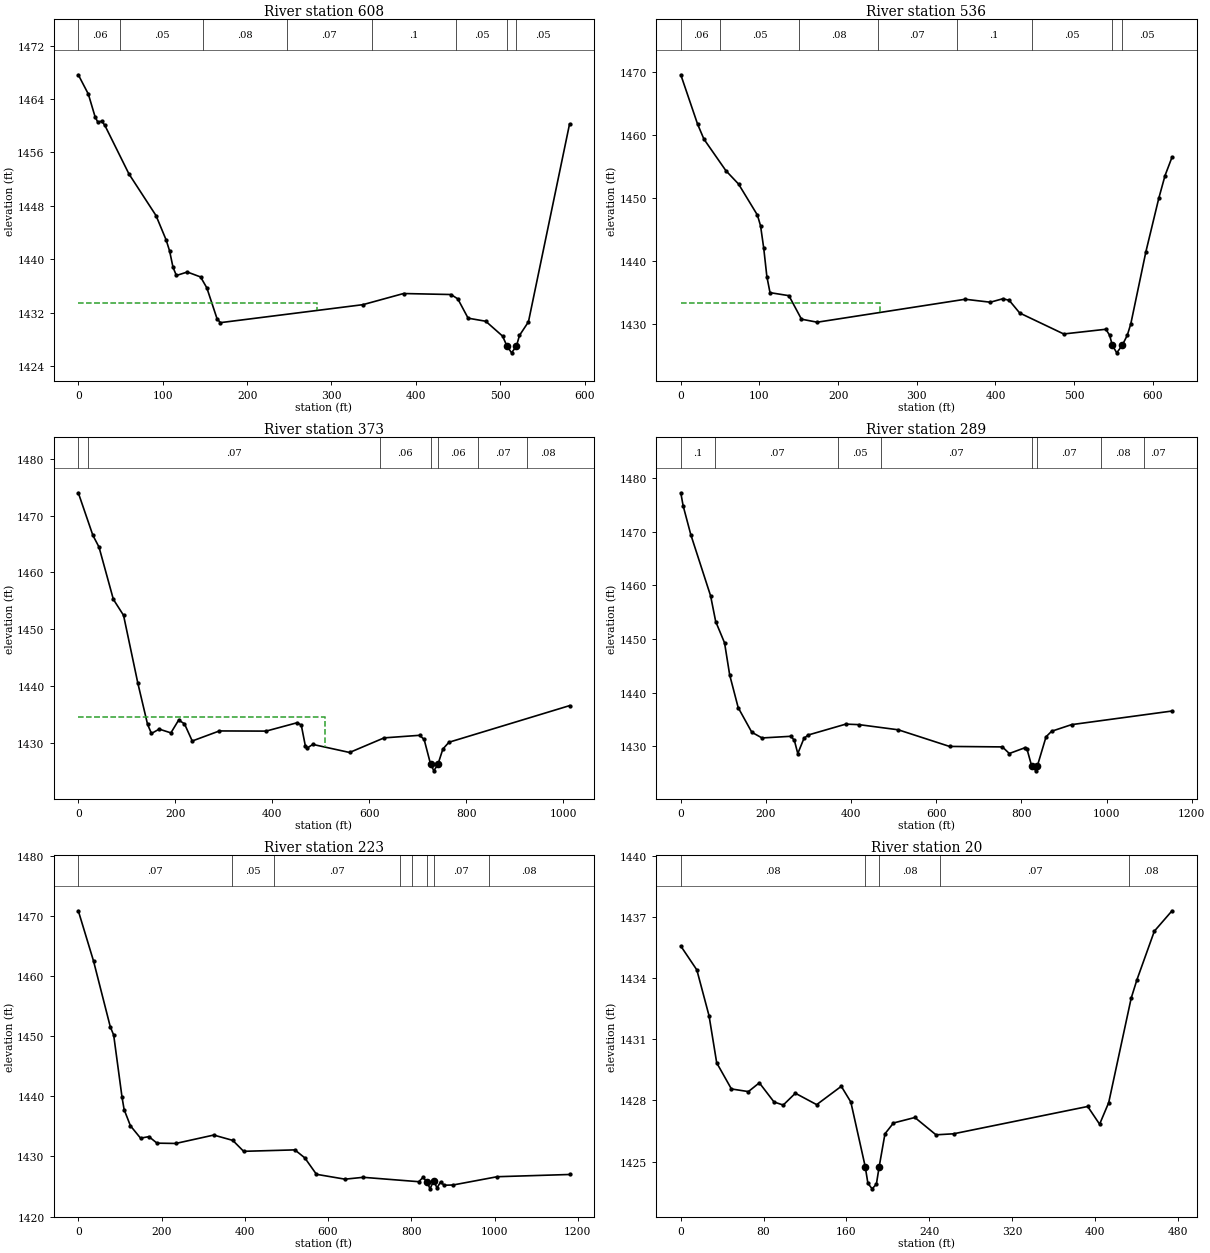
Type RM Length L Ch R = 1 ,608     ,70.3,72.5,74.3
XS GIS Cut Line= 4
2170852.06703088733383.1746508342170784.55729168733386.483473281
2170396.65794902 733423.05435255 2170296.7886777733498.044453575
#Sta/Elev= 30
       0 1467.62    11.9 1464.73    19.9 1461.33      23 1460.56    27.9 1460.67
    31.5 1460.04      60 1452.78    92.1 1446.54   104.1 1442.89   108.2 1441.24
   112.2 1438.82   116.2 1437.57   129.2 1438.09   144.9 1437.35   152.3 1435.72
   164.4  1431.1   168.4 1430.51   337.2  1433.2   385.4 1434.87   441.6 1434.72
   449.7 1434.07   461.9 1431.18   482.8 1430.72   502.8 1428.49   507.8 1427.04
   513.4 1425.99   519.1 1426.98   522.8  1428.6   533.4 1430.63   582.1 1460.24
#Mann= 8 ,-1,0
       0     .06       0      50     .05       0  147.59     .08       0
  247.59     .07       0  347.59      .1       0  447.59     .05       0
   507.8    .045       0   519.1     .05       0
#XS Ineff= 2 , 0
          282.65 1433.45
Permanent Ineff=
       F       F
Bank Sta=507.8,519.1
XS Rating Curve= 0 ,0
Exp/Cntr(USF)=0,0
Exp/Cntr=0.3,0.1

Type RM Length L Ch R = 1 ,536     ,160.9,162.6,164.3
XS GIS Cut Line= 5
2170849.53234847733345.8320939172170809.12974236733344.045126844
2170413.06359038733346.6328405822170284.90674583733411.514197655
2170249.94791395733438.647548239
#Sta/Elev= 30
       0 1469.59    21.4 1461.72    29.4 1459.36    57.4 1454.33    73.4 1452.22
    97.4 1447.28   101.4 1445.56   105.4 1442.03   109.4 1437.51   113.4 1434.95
   137.4 1434.47   153.4 1430.73   173.4 1430.25   361.4  1433.9   393.4 1433.43
   409.4 1433.98   417.4 1433.73   430.8 1431.71   486.7 1428.38   540.3 1429.13
   545.1 1428.17   548.4 1426.61   554.1 1425.38   561.1 1426.58   567.5 1428.17
     572    1430   591.2 1441.48   607.5 1449.93   615.5 1453.57   624.4  1456.5
#Mann= 8 ,-1,0
       0     .06       0   50.44     .05       0  150.44     .08       0
  250.44     .07       0  350.44      .1       0  446.52     .05       0
   548.4    .045       0   561.1     .05       0
#XS Ineff= 2 , 0
          253.28 1433.31
Permanent Ineff=
       F       F
Bank Sta=548.4,561.1
XS Rating Curve= 0 ,0
Exp/Cntr(USF)=0,0
Exp/Cntr=0.3,0.1

Type RM Length L Ch R = 1 ,373     ,85.5,84.1,82.4
XS GIS Cut Line= 6
2170916.87528757733226.293169117 2170799.1732009733187.867097138
2170482.21696631733198.9274584172170214.57567733733273.279866344
2170171.28366073733289.4941109212169925.81048247733323.066127579
#Sta/Elev= 30
       0 1474.02      30 1466.55    42.7 1464.47    72.3 1455.27    93.3 1452.46
   122.8 1440.51   142.8 1433.28   150.8 1431.67   166.8 1432.44   190.9 1431.78
   206.9 1434.03   218.9 1433.37   234.9 1430.35   290.9 1432.12   387.1 1432.09
   451.4 1433.57   459.7 1433.14     468 1429.52   472.1 1429.12   483.4 1429.75
   559.3 1428.33   630.4  1430.9   703.4 1431.35   712.9 1430.64   726.21426.285
     733  1425.1   741.31426.226   751.6 1428.94   764.1 1430.13  1012.7 1436.57
#Mann= 7 ,-1,0
       0      .1       0      20     .07       0  620.96     .06       0
   726.2    .045       0   741.3     .06       0  824.97     .07       0
  924.97     .08       0
#XS Ineff= 2 , 0
          508.23 1434.54
Permanent Ineff=
       F       F
Bank Sta=726.2,741.3
XS Rating Curve= 0 ,0
Exp/Cntr(USF)=0,0
Exp/Cntr=0.3,0.1

Type RM Length L Ch R = 1 ,289     ,65.8,66.3,67.4
XS GIS Cut Line= 6
2170965.00473084733165.291120623 2170885.2250726733124.131966801
2170463.16764364733121.2387084142170170.63174117 733199.91953115
2170132.70379269733220.511017802 2169851.1659014733310.512928389
#Sta/Elev= 30
       0 1477.28     5.4 1474.89    23.4  1469.5      70 1458.07      82 1453.27
   102.8  1449.3   114.8 1443.33   134.8 1437.23   166.8 1432.64   190.8 1431.58
   258.8 1431.89   266.8 1431.11   274.8 1428.67   289.2 1431.49   298.8 1432.12
   387.7 1434.16   418.8 1434.06   510.8  1433.1   631.2    1430   755.3 1429.91
   771.6 1428.68   809.1 1429.78   813.2 1429.48   824.31426.306   834.2 1425.45
   837.1 1426.27   857.9  1431.8     871 1432.83   917.7 1434.06  1153.8  1436.6
#Mann= 8 ,-1,0
       0      .1       0      80     .07       0  369.77     .05       0
  469.77     .07       0   824.3    .045       0   837.1     .07       0
  987.94     .08       0 1087.94     .07       0
Bank Sta=824.3,837.1
XS Rating Curve= 0 ,0
Exp/Cntr(USF)=0,0
Exp/Cntr=0.3,0.1

Type RM Length L Ch R = 1 ,223     ,201.1,202.3,203.4
XS GIS Cut Line= 4
2170968.47354957733123.6402984992170400.63364322733053.752310026
2170086.13769509733167.3202912942169817.81773935733220.984282443
#Sta/Elev= 30
       0 1470.93    36.6 1462.56    76.9 1451.59      85 1450.23   105.1 1439.86
   110.1 1437.81   125.2 1435.12   149.6 1433.05   169.6 1433.31   189.1 1432.22
   234.1 1432.17   325.4 1433.57   371.1 1432.68   397.2 1430.86   520.2  1431.1
   544.1 1429.77   572.1 1427.03   640.7 1426.22   684.5 1426.53   817.8  1425.8
   828.2 1426.52   838.61425.672   844.8 1424.61   853.71425.885   861.8 1424.78
   870.3 1425.76   878.8 1425.21   900.2 1425.25  1006.4 1426.63  1180.1    1427
#Mann= 8 ,-1,0
       0     .07       0     370     .05       0     470     .07       0
  772.12     .08       0  802.12     .07       0   838.6    .045       0
   853.7     .07       0   986.5     .08       0
Bank Sta=838.6,853.7
XS Rating Curve= 0 ,0
Exp/Cntr(USF)=0,0
Exp/Cntr=0.3,0.1

Type RM Length L Ch R = 1 ,20      ,,,
XS GIS Cut Line= 6
2170248.70413808732943.0581483172170221.91321718732921.005445604
2170098.18889369732951.7052840392170051.30189959732963.558492237
2169855.60074784733017.6653123322169812.97890084733061.416860529
#Sta/Elev= 30
       0 1435.57    15.5  1434.4    27.3 1432.15    34.7 1429.84    48.9 1428.56
    65.3 1428.43    75.9 1428.86    90.1 1427.92      99 1427.77   110.7 1428.35
   131.3 1427.79   155.1 1428.69   164.3 1427.92   178.21424.753   180.8 1423.93
   184.9 1423.66     189 1423.89   191.71424.746   197.3 1426.36   205.5 1426.89
   226.2 1427.16   246.6 1426.31   263.6 1426.36   393.2  1427.7   404.7 1426.83
   413.5 1427.89   435.2 1433.01   440.8 1433.92   457.6  1436.3   474.7  1437.3
#Mann= 5 ,-1,0
       0     .08       0   178.2    .045       0   191.7     .08       0
  250.54     .07       0  433.58     .08       0
Bank Sta=178.2,191.7
XS Rating Curve= 0 ,0
Exp/Cntr(USF)=0,0
Exp/Cntr=0.3,0.1
LCMann Table=0

Chan Stop Cuts=-1
Use User Specified Reach Order=0
Composite Channel Slope=5